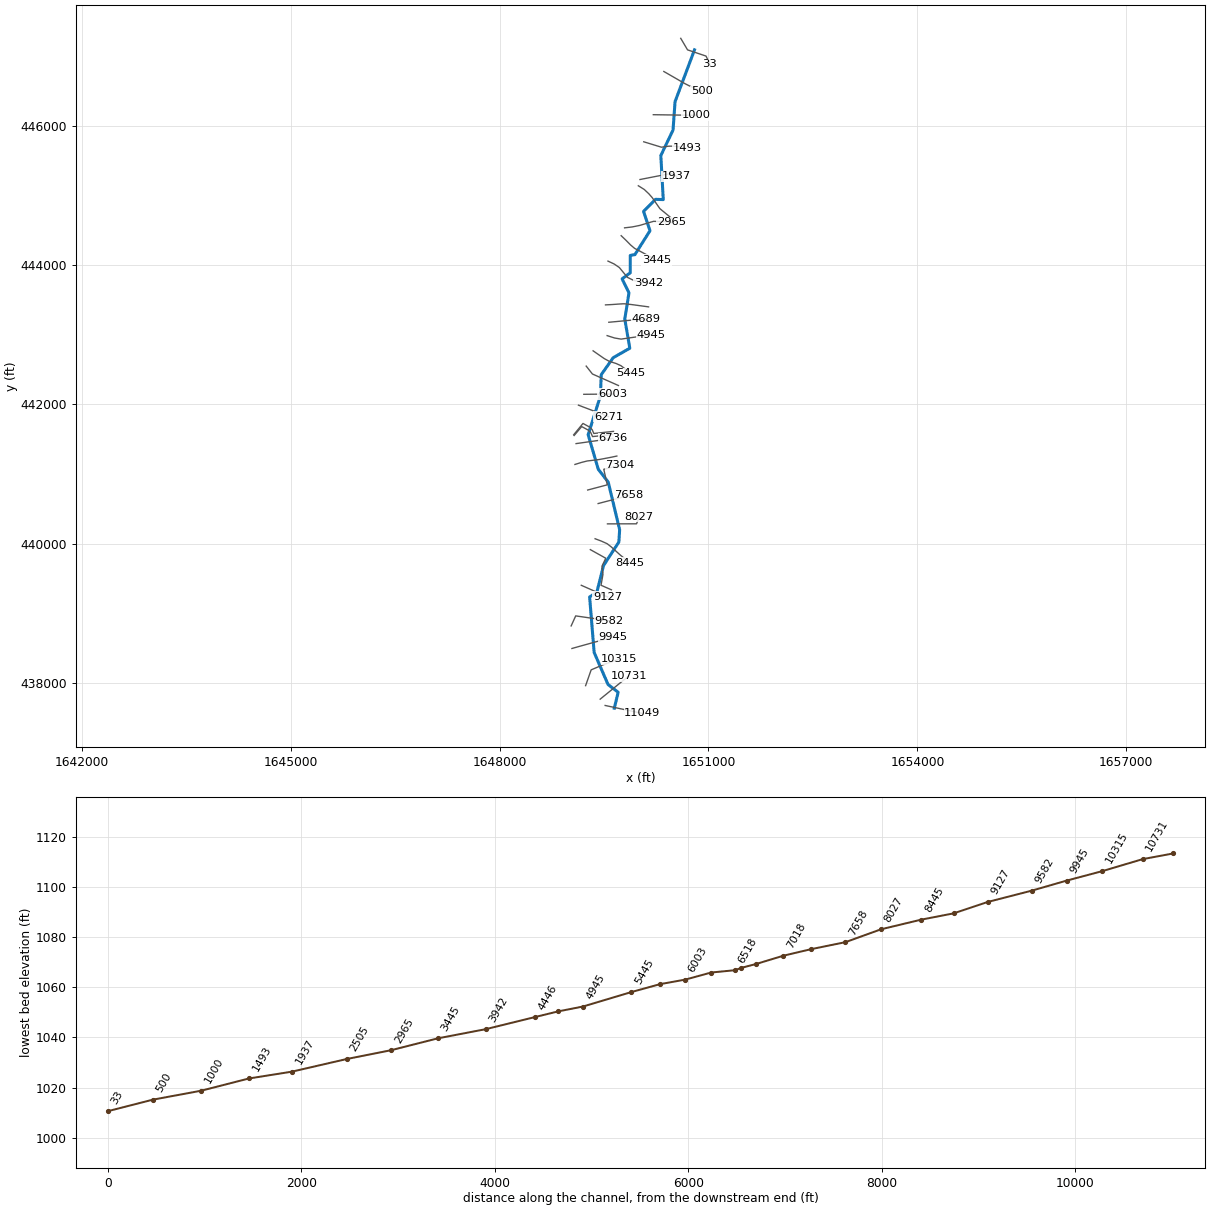
--- LAURELRN.prj (project) ---

Proj Title=LAURELRN
Current Plan=p01
Default Exp/Contr=0,0
English Units
Geom File=g01
Flow File=f01
Plan File=p01
BEGIN DESCRIPTION:
---------- MODELED AS PART OF WVEMD CTP PROGRAM, 2023----------
Stream Name: Laurel Run
Flood Zone:  AFH
Wetzel County, WV
HEC-RAS Version: RAS 6.3
Vertical Datum: NAVD88
Projection: NAD 1983 StatePlane West Virginia S FIPS 4702 (US Feet)
Terrain: 1-meter West Virginia FEMA R3 South Central (collected 2018-2020)
Land Use: 2019 NLCD
Hydrologic Method:
WV 2010 Regional Regression Equations
Additional Model Notes:
None
END DESCRIPTION:
DSS Export Rating Curves= 0
DSS Export Rating Curve Sorted= 0
DSS Export Volume Flow Curves= 0
DXF OffsetX= 0
DXF OffsetY= 0
DXF ScaleX= 0
DXF ScaleY= 0

--- LAURELRN.p01 (plan) ---

Plan Title=Floodplain
Program Version=4.00
Geom File=g01
Flow File=f01
K Sum by GR=0
Std Step Tol=0.01
Critical Tol=0.01
Num of Std Step Trials=20
Max Error Tol=0.3
Flow Tol Ratio=0.001
Split Flow NTrial=30
Split Flow Tol=0.02
Split Flow Ratio=0.02
Log Output Level=0
Friction Slope Method=1
Unsteady Friction Slope Method=2
Unsteady Bridges Friction Slope Method=1
Global Log Level=0
CheckData=False
Run HTab=0
Run UNet=0
Run PostProcess=0
UNET Theta=0
UNET Theta Warmup=0
UNET ZTol=0
UNET ZSATol=0
UNET MxIter=0
UNET MaxInSteps=0
UNET DtIC=0
UNET DtMin=0
UNET MaxCRTS=0
UNET WFStab=0
UNET SFStab=0
UNET WFX=0
UNET SFX=0
UNET DSS MLevel=0
UNET DZMax Abort=0
UNET Convert EG Bridges=0
UNET Use Existing IB Tables=0
UNET Froude Limit=0
UNET Froude Power=0
Write IC File=0
Echo Input=False
Echo Output=False
Write Detailed=0

--- LAURELRN.f01 (steady flow) ---

Flow Title=Flow
Program Version=4.00
Number of Profiles=1
Profile Names=F01pct
River Rch & RM=LAURELRN,Main,11049
     682
River Rch & RM=LAURELRN,Main,8027
     854
River Rch & RM=LAURELRN,Main,5742
     954
River Rch & RM=LAURELRN,Main,4945
    1060
River Rch & RM=LAURELRN,Main,2505
    1180
Boundary for River Rch & Prof#=LAURELRN,Main      ,1
Up Type=0
Dn Type=3
Dn Slope=0.008001

--- LAURELRN.g01 (geometry) ---

Geom Title=Geometry
Program Version=6.31

River Reach=LAURELRN        ,Main
Reach XY= 30
     1649647.643      437636.668     1649703.106      437864.785
1649557.37482215 437976.95527405     1649358.424      438436.016
     1649292.935      439233.798     1649396.966      439302.107
     1649493.163      439685.331     1649713.133      440022.178
       1649724.1       440199.22     1649560.533      440882.629
     1649417.333      441067.504      1649271.94      441563.846
     1649448.668      442120.663     1649459.948       442425.55
     1649631.976      442669.647     1649869.806      442805.013
     1649798.363      443224.271     1649858.212      443600.601
     1649759.821       443800.83     1649876.386      443888.567
     1649876.386      444137.364     1649943.443      444149.271
     1650160.279      444493.013     1650067.528      444770.638
     1650240.809      444943.292     1650350.794      444939.219
     1650315.699       445572.18     1650491.173      445938.482
     1650520.001       446346.46     1650799.409      447090.307

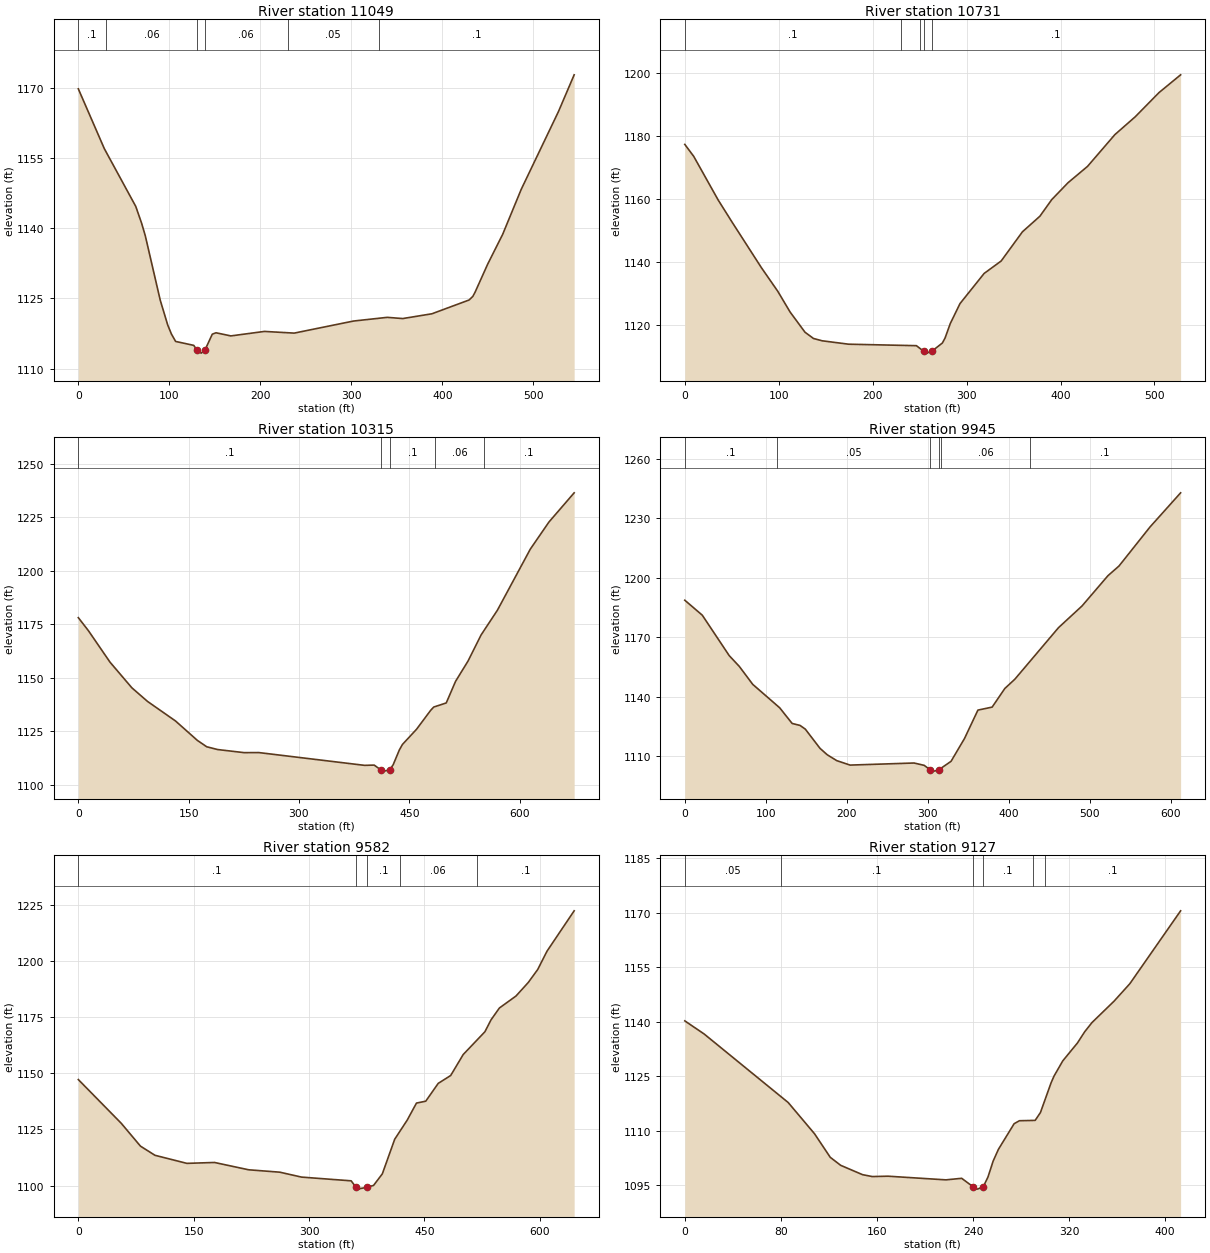
Type RM Length L Ch R = 1 ,11049   ,314.3,317.7,321.8
XS GIS Cut Line= 2
1649516.10394971437675.3293682291650048.98060399437561.836368841
#Sta/Elev= 30
       0 1169.82    28.6 1157.02    63.1 1144.69    69.5 1141.12    73.6  1138.4
      90 1124.64    98.2 1119.35   102.3  1117.4   106.9 1115.82   126.8 1114.98
  130.55 1113.95     135 1113.32   139.1 1113.96   147.2 1117.37   151.3 1117.67
   167.6    1117   204.5 1117.96   237.2  1117.6   302.4 1120.18   339.5 1120.97
   356.4 1120.71   388.5 1121.73   429.4 1124.68   433.5 1125.45   435.9 1126.32
   449.9 1132.38   466.2 1138.68   486.7 1148.35   527.6 1164.97544.8286 1172.82
#Mann= 6 ,-1,0
       0      .1       0      30     .06       0  130.55    .045       0
   139.1     .06       0     230     .05       0     330      .1       0
Bank Sta=130.55,139.1
XS Rating Curve= 0 ,0
Exp/Cntr(USF)=0,0
Exp/Cntr=0.3,0.1

Type RM Length L Ch R = 1 ,10731   ,414.3,416,410.1
XS GIS Cut Line= 2
1649444.76549296 437766.123767741649854.42117646438099.036565946
#Sta/Elev= 30
       0 1177.43     9.5 1173.63    35.5 1159.76    50.7 1152.54    81.6  1138.2
      99 1130.71   112.1 1124.12     128 1117.68     137  1115.7   146.3 1114.96
   174.4 1113.88   246.6 1113.41   254.3 1111.63   257.2 1111.04   262.9 1111.62
   274.2 1114.25   277.1 1115.85   282.6 1120.42     293  1126.8   318.7 1136.39
   336.8 1140.34   359.5 1149.64     378 1154.57   390.7 1159.88   407.9 1165.21
   428.8 1170.45   457.9 1180.55   479.5  1186.2   504.9 1193.92527.8719 1199.56
#Mann= 5 ,-1,0
       0      .1       0     230     .06       0     250      .1       0
   254.3    .045       0   262.9      .1       0
Bank Sta=254.3,262.9
XS Rating Curve= 0 ,0
Exp/Cntr(USF)=0,0
Exp/Cntr=0.3,0.1

Type RM Length L Ch R = 1 ,10315   ,369.6,370.5,367.8
XS GIS Cut Line= 6
  1649235.510551437959.8381073661649315.21681522438186.584290621
1649476.32344838438255.4653864481649547.75375171438281.118222294
 1649631.2263538438310.2270879571649720.51095213438340.830045116
#Sta/Elev= 30
       0 1178.03    13.6    1172    43.1 1157.22    72.8 1145.23      94 1138.89
   132.2 1129.71   161.9 1120.63   174.6 1117.66   189.3 1116.37   225.5 1114.91
   245.3 1114.95   389.2 1108.97   402.3 1109.09     411 1106.96   416.2 1106.27
  423.56 1106.95   428.1 1109.23   436.6 1116.22   440.8 1118.76   459.9 1125.84
   479.1 1134.69   483.3 1136.24   500.3 1138.15     513 1148.27     530 1157.78
   547.8 1170.01   569.8 1181.47   614.6 1210.07     640 1222.77674.2447 1236.41
#Mann= 5 ,-1,0
       0      .1       0     411    .045       0  423.56      .1       0
  485.56     .06       0  551.46      .1       0
Bank Sta=411,423.56
XS Rating Curve= 0 ,0
Exp/Cntr(USF)=0,0
Exp/Cntr=0.3,0.1

Type RM Length L Ch R = 1 ,9945    ,364,362.2,358.6
XS GIS Cut Line= 6
1649039.35041125438493.6180613341649129.52509968438519.270241007
1649213.85531159438542.6071365921649454.79971159438609.283840507
1649539.13057968438632.6210641711649629.48472968438657.624951169
#Sta/Elev= 30
       0  1188.6    21.6 1181.06    54.9 1160.66    67.3 1155.26    83.9 1146.21
   117.2  1134.4   132.6  1126.5   142.4  1125.5   148.9 1123.62     167 1113.97
     176  1110.7   187.7 1107.76   204.2 1105.51   283.2 1106.56   295.7 1105.38
  303.33 1103.08   308.1 1102.47  313.52 1103.08   328.9 1107.41   345.5 1118.89
   362.1 1133.22   379.7 1134.74   395.3  1144.1   407.7 1148.78   461.7 1174.79
   490.7  1185.7   522.7 1200.94   536.4 1205.85   574.7 1225.51612.5024 1242.72
#Mann= 6 ,-1,0
       0      .1       0  113.75     .05       0  303.33    .045       0
  313.52     .05       0  316.25     .06       0  426.25      .1       0
Bank Sta=303.33,313.52
XS Rating Curve= 0 ,0
Exp/Cntr(USF)=0,0
Exp/Cntr=0.3,0.1

Type RM Length L Ch R = 1 ,9582    ,454.8,455.4,452.5
XS GIS Cut Line= 3
1649027.95355123438817.7101895491649093.26632963438961.650360437
1649575.06853946438891.845011802
#Sta/Elev= 30
       0  1147.2    55.8 1127.76    80.8 1117.59    99.7 1113.51   141.2 1109.92
   177.1 1110.32   221.6 1107.06     262    1106   290.3 1103.81   354.9 1102.15
   361.1 1099.29     363 1098.46   375.2 1099.28     384 1100.11   395.4 1105.26
   411.5 1120.66   427.7 1129.13   439.8 1136.74   451.9 1137.59   468.1 1145.51
   484.3 1149.01   500.6 1158.34   528.8 1168.47   536.8 1173.79   547.7 1179.06
   569.2 1184.36   585.2 1190.39   597.5 1196.18   609.6 1204.33   644.9 1222.28
#Mann= 5 ,-1,0
       0      .1       0   361.1    .045       0   375.2      .1       0
  418.06     .06       0  518.06      .1       0
Bank Sta=361.1,375.2
XS Rating Curve= 0 ,0
Exp/Cntr(USF)=0,0
Exp/Cntr=0.3,0.1

Type RM Length L Ch R = 1 ,9127    ,354.5,350.5,341.3
XS GIS Cut Line= 2
1649173.40043458439401.0804922691649550.80516399439233.824919782
#Sta/Elev= 30
       0 1140.27    16.1 1136.66    86.1 1117.78     108 1109.19   121.1  1102.7
   129.8 1100.49     148 1097.92   156.1  1097.4   169.2  1097.5   217.4 1096.49
   230.5 1096.92     240  1094.6   243.6 1093.94  248.48 1094.58   252.4 1097.26
   256.7 1101.64   261.1 1104.89   274.2 1111.96   278.6 1112.77   291.7 1112.87
   296.1 1115.03   304.9 1123.17   307.4 1125.06   314.7 1129.26   326.9 1134.18
   332.9 1137.25     339  1139.8   357.4  1145.7   370.5 1150.49 412.806 1170.57
#Mann= 6 ,-1,0
       0     .05       0      80      .1       0     240    .045       0
  248.48      .1       0     290     .06       0     300      .1       0
Bank Sta=240,248.48
XS Rating Curve= 0 ,0
Exp/Cntr(USF)=0,0
Exp/Cntr=0.3,0.1

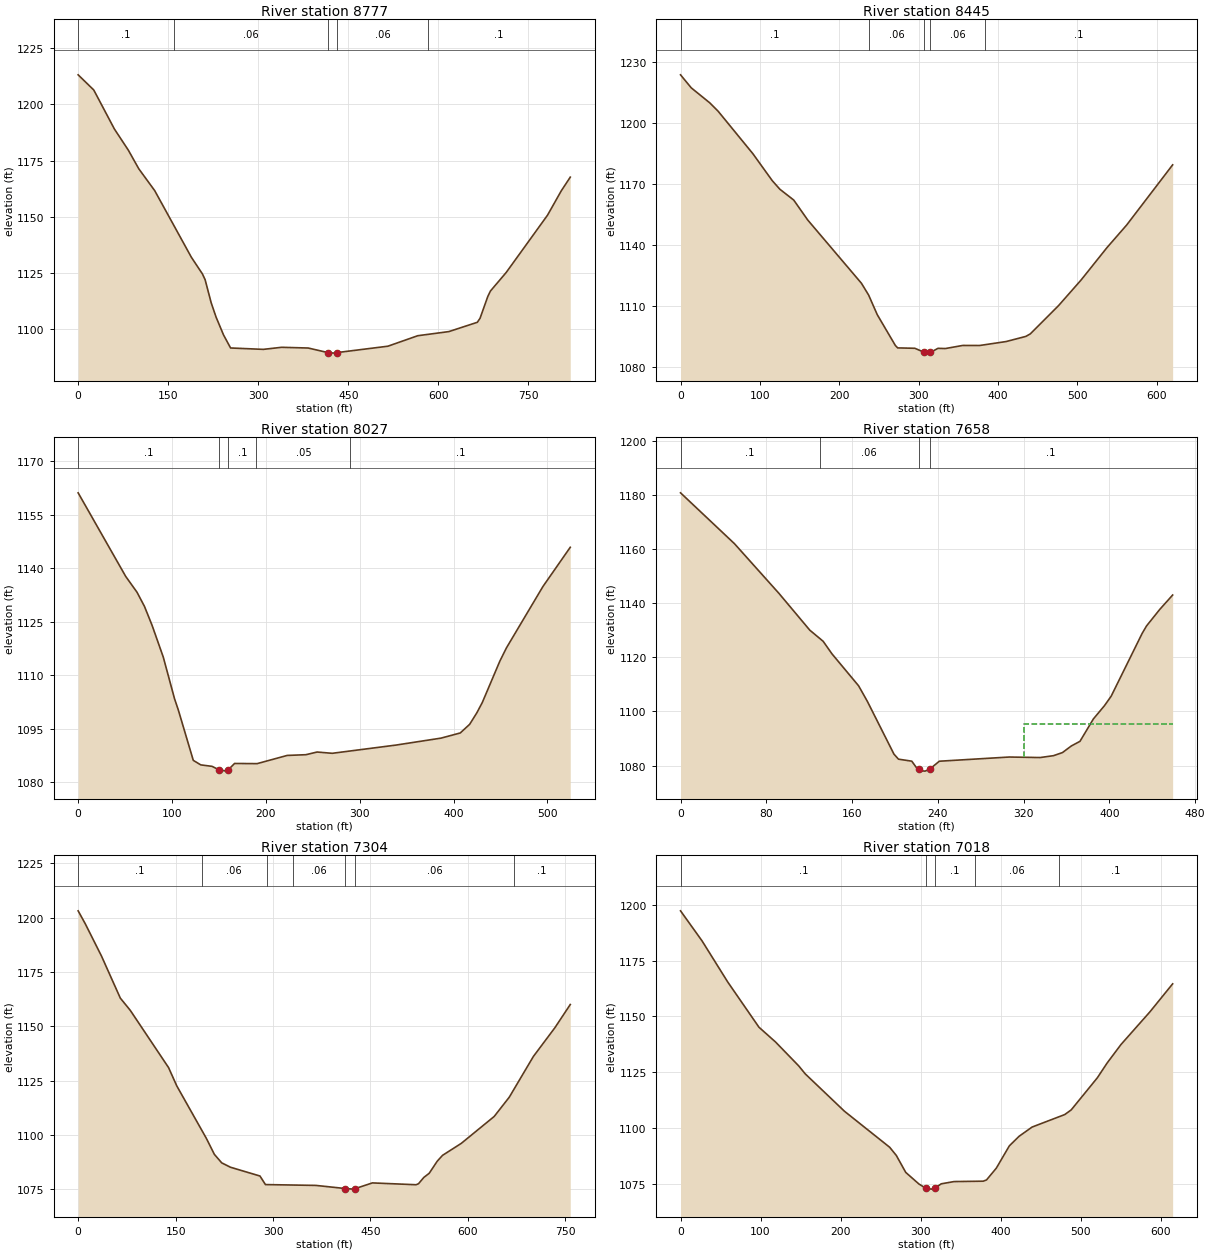
Type RM Length L Ch R = 1 ,8777    ,327.7,331.9,338.8
XS GIS Cut Line= 6
1649303.33480366439913.1846913761649525.13255104439789.639454899
1649471.62870847439677.7677840741649484.27507126439554.222547597
1649457.03675141439401.4933969921649605.87471346439336.315988772
#Sta/Elev= 30
       0 1213.16      26 1206.42    60.4 1189.06    83.5 1179.71     101 1171.39
   127.5 1161.68   188.6 1132.04   207.1  1124.6   211.5 1122.06   221.6  1111.8
   229.8  1105.4   242.2  1097.5   253.9 1091.71   308.3 1091.09     339 1092.01
   383.2 1091.69   415.9 1089.66   426.9 1089.42  431.27 1089.66     516  1092.5
   565.7 1097.16   617.6    1099   664.9 1103.13   669.4 1104.89   682.4 1114.64
   686.8 1117.05     713 1125.28   781.8 1150.74   804.7 1161.57819.7061 1167.66
#Mann= 5 ,-1,0
       0      .1       0     160     .06       0   415.9    .045       0
  431.27     .06       0  582.08      .1       0
Bank Sta=415.9,431.27
XS Rating Curve= 0 ,0
Exp/Cntr(USF)=0,0
Exp/Cntr=0.3,0.1

Type RM Length L Ch R = 1 ,8445    ,411.8,417.9,418.6
XS GIS Cut Line= 6
1649371.76575692440069.5309199991649463.06544308 440035.13269484
1649545.31593476439997.8545541761649604.67441183439951.689620256
1649734.49042517439834.2928734271649875.98029967439720.226500511
#Sta/Elev= 30
       0 1223.83    13.5 1217.43    36.9 1210.03    47.4 1205.91    91.1 1185.05
   115.4 1171.85   125.1 1167.56   142.6 1162.23   160.2 1152.43   227.9 1121.29
     237 1115.46   247.8 1105.86   270.6 1090.71   273.5 1089.51   295.2 1089.32
   307.3 1087.28   311.6 1086.94  314.72 1087.27   324.3  1089.3   333.5 1089.19
   355.5 1090.72   376.9  1090.7   410.2 1092.64   434.9 1095.16   440.5 1096.38
   476.2 1110.33   504.6 1122.93   537.2 1138.86   561.9 1149.93619.8707 1179.55
#Mann= 5 ,-1,0
       0      .1       0  237.87     .06       0   307.3    .045       0
  314.72     .06       0  383.07      .1       0
Bank Sta=307.3,314.72
XS Rating Curve= 0 ,0
Exp/Cntr(USF)=0,0
Exp/Cntr=0.3,0.1

Type RM Length L Ch R = 1 ,8027    ,366.4,368.5,368.5
XS GIS Cut Line= 3
1649549.42959728440282.9979989421649966.65148074 440284.07888465
1650006.64425196440383.520369829
#Sta/Elev= 30
       0 1161.17    50.7 1137.71    62.7 1133.29    70.7 1129.29    78.7 1124.05
    90.7 1115.09   102.7 1103.41   106.7 1100.28   122.7  1086.1   130.7 1084.83
   142.7 1084.42  150.27 1083.42   158.7 1083.08   159.8 1083.42   166.7 1085.23
   190.7 1085.18   222.7 1087.48   242.7 1087.69   254.7 1088.44   270.7 1088.08
   338.7 1090.39   386.7 1092.34   407.2 1093.79   417.2 1096.21   424.8 1099.42
   430.7 1102.35   449.4 1113.96   456.5 1117.71   495.3 1134.89524.4055 1145.89
#Mann= 5 ,-1,0
       0      .1       0  150.27    .045       0   159.8      .1       0
     190     .05       0     290      .1       0
Bank Sta=150.27,159.8
XS Rating Curve= 0 ,0
Exp/Cntr(USF)=0,0
Exp/Cntr=0.3,0.1

Type RM Length L Ch R = 1 ,7658    ,352.7,354.2,368.3
XS GIS Cut Line= 2
1649415.39976943440574.8371402261649859.64379561440690.491911031
#Sta/Elev= 30
       0 1180.79    50.3    1162    91.7 1143.68   120.6 1130.03     133 1125.94
   141.3 1121.27   166.1 1109.48   174.3 1103.71   199.1 1084.22   203.3 1082.36
   215.7 1081.62   219.8 1079.38   222.1 1078.64   223.9  1078.1   228.1 1077.94
  232.28 1078.63   241.4  1081.6   306.6 1083.15   335.5 1082.96   347.9 1083.65
   356.3  1084.8   364.5 1087.23   372.6 1088.95   385.1 1097.22   395.4  1102.1
   401.7 1105.63   430.6 1128.83   434.7  1131.6   447.1 1137.73 459.052 1143.02
#Mann= 4 ,-1,0
       0      .1       0     130     .06       0   222.1    .045       0
  232.28      .1       0
#XS Ineff= 2 , 0
                          320.48         1095.51
Permanent Ineff=
       F       F
Bank Sta=222.1,232.28
XS Rating Curve= 0 ,0
Exp/Cntr(USF)=0,0
Exp/Cntr=0.3,0.1

Type RM Length L Ch R = 1 ,7304    ,289.7,286.5,270.1
XS GIS Cut Line= 4
  1649265.356849440769.1236809191649546.72330806440843.462603053
1649496.52494682441067.082361857   1649727.19909441122.828112198
#Sta/Elev= 30
       0  1203.2    11.1 1197.17      36 1182.35    64.9 1163.05    80.3 1157.39
   139.2 1131.07   151.8 1122.67   197.3 1098.55   209.7 1091.15     221 1087.25
   234.5 1085.23   279.9 1081.19   288.3 1077.25   365.9 1076.87   411.3 1075.43
   423.3 1075.16  426.86 1075.44   452.9 1078.02   520.2 1077.18   523.9 1077.63
   532.1 1080.54   540.4 1082.45   552.7 1087.99   560.9  1090.7   589.7  1096.2
   640.4 1108.58   663.6 1117.44   700.8 1136.22   733.8 1149.39757.5205 1160.09
#Mann= 7 ,-1,0
       0      .1       0     190     .06       0     290      .1       0
  331.02     .06       0   411.3    .045       0  426.86     .06       0
  670.21      .1       0
Bank Sta=411.3,426.86
XS Rating Curve= 0 ,0
Exp/Cntr(USF)=0,0
Exp/Cntr=0.3,0.1

Type RM Length L Ch R = 1 ,7018    ,281.6,281.9,282.4
XS GIS Cut Line= 6
1649082.45347802441136.2937421121649172.50447902441164.335352695
1649257.64702527 441185.980650611649431.52102135441207.126277602
1649592.08041151441237.3663746031649684.12353451441256.946716032
#Sta/Elev= 30
       0 1197.33    26.9 1183.85      59 1165.41      98 1145.14   118.7 1138.52
   147.6 1127.83   155.8 1124.23   204.8 1107.47   261.3 1091.32   269.6 1087.65
   281.4 1080.03   297.9 1074.84  306.78 1072.87   313.6 1072.55   317.6  1072.9
   325.7 1074.93   341.8 1075.94   378.2 1076.11   382.3 1076.68   394.5 1081.94
   410.8 1091.95   422.9 1096.22   439.2 1100.38     480 1105.98   488.1 1108.08
   520.7 1122.45     533 1129.11   550.4 1137.44   586.2 1151.94614.8135 1164.59
#Mann= 5 ,-1,0
       0      .1       0  306.78    .045       0   317.6      .1       0
  367.32     .06       0  472.77      .1       0
Bank Sta=306.78,317.6
XS Rating Curve= 0 ,0
Exp/Cntr(USF)=0,0
Exp/Cntr=0.3,0.1

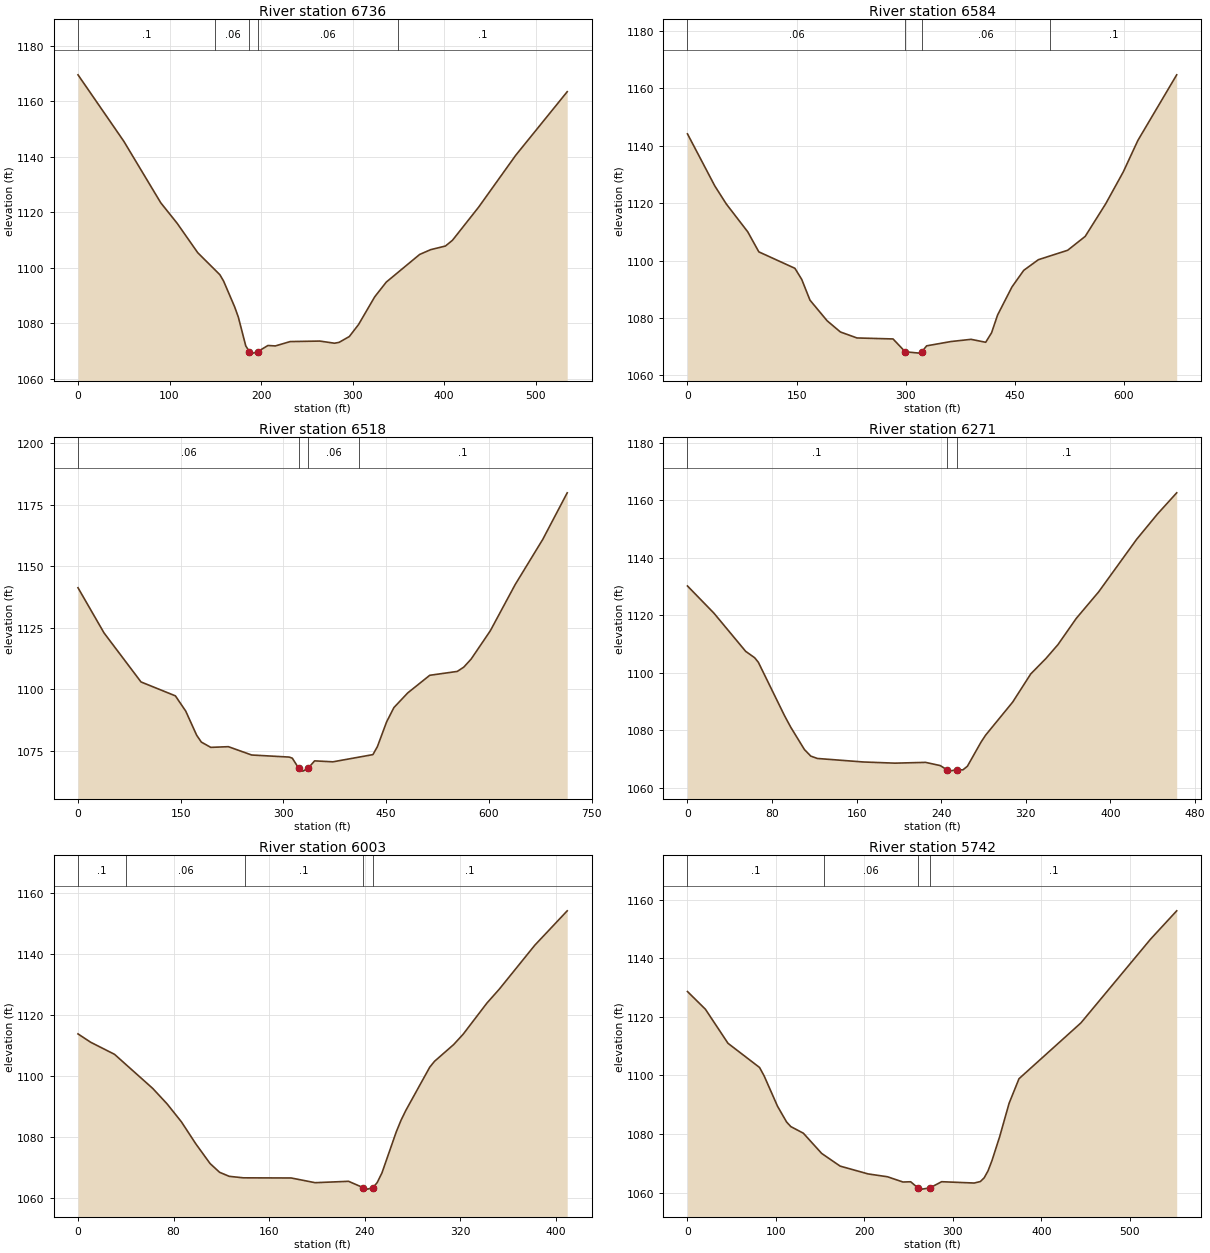
Type RM Length L Ch R = 1 ,6736    ,165,151.7,146.5
XS GIS Cut Line= 2
1649098.63012531441435.6416519331649627.83176817441510.547031529
#Sta/Elev= 30
       0 1169.47      50 1145.57    90.4  1123.4   108.3 1116.02   130.8 1105.42
     155 1097.48   159.1 1095.18   171.2 1085.86   175.2 1082.18   183.3 1071.84
   187.3 1069.76   191.4 1069.25  196.18 1069.75   207.5    1072   215.6 1071.84
   231.8 1073.41   264.2 1073.59   280.2 1072.82   285.2 1073.12   296.4 1075.22
   306.5 1079.54   324.2 1089.54   336.8 1094.83   373.2 1104.77   385.3 1106.51
   401.4 1107.81   409.1 1109.88   437.8 1121.86   478.2 1140.49534.4766 1163.39
#Mann= 5 ,-1,0
       0      .1       0     150     .06       0   187.3    .045       0
  196.18     .06       0     350      .1       0
Bank Sta=187.3,196.18
XS Rating Curve= 0 ,0
Exp/Cntr(USF)=0,0
Exp/Cntr=0.3,0.1

Type RM Length L Ch R = 1 ,6584    ,58.7,66.4,66.2
XS GIS Cut Line= 6
1649070.47905752441551.8969147981649179.43233694441680.306136964
1649275.73925356441627.7750915321649310.75995051441591.781597441
1649335.07987895441536.3321605971649617.19104886441566.488871863
#Sta/Elev= 30
       0 1144.15    37.6 1125.99    53.3 1119.74    82.9 1109.99    98.1 1103.02
   147.7 1097.29   157.1 1093.41   168.4 1086.19     192    1079   210.2  1075.1
     233 1073.01   282.6 1072.66   299.4 1068.18   318.8 1067.72  322.19 1068.18
   328.8 1070.26   362.2 1071.76   389.9 1072.53     410  1071.5   418.1 1074.83
   426.3 1080.99   446.2 1090.83   462.3 1096.58   482.4 1100.29   522.7 1103.58
   546.8 1108.42     575 1119.79   599.1 1130.88   619.2 1141.86672.5916 1164.74
#Mann= 4 ,-1,0
       0     .06       0   299.4    .045       0  322.19     .06       0
  498.87      .1       0
Bank Sta=299.4,322.19
XS Rating Curve= 0 ,0
Exp/Cntr(USF)=0,0
Exp/Cntr=0.3,0.1

Type RM Length L Ch R = 1 ,6518    ,242.6,246.2,248.5
XS GIS Cut Line= 6
 1649064.6422747441562.5976833121649197.91548255441725.054805294
1649294.22239917441672.5237598631649329.24309613441636.530265771
1649353.56302457441581.0808289271649635.67419448441611.237540193
#Sta/Elev= 30
       0 1141.27      38 1122.92      92    1103   142.2 1097.35   157.3 1091.16
   173.2 1081.39   180.1 1078.56   193.9 1076.42   219.6  1076.7   253.6 1073.32
   308.3 1072.48   312.9 1072.04   322.5 1067.84   328.3 1066.77   335.6 1067.84
   345.5 1070.94   372.2 1070.55   430.6 1073.48   437.2 1076.75   450.6 1086.77
   461.3  1092.6   481.4 1098.53   513.6  1105.7   553.8 1107.28   563.3 1109.02
     574 1112.28   602.1 1123.82   638.3 1142.54   678.6 1160.91714.3168 1179.83
#Mann= 4 ,-1,0
       0     .06       0   322.5    .045       0   335.6     .06       0
  410.05      .1       0
Bank Sta=322.5,335.6
XS Rating Curve= 0 ,0
Exp/Cntr(USF)=0,0
Exp/Cntr=0.3,0.1

Type RM Length L Ch R = 1 ,6271    ,267.3,268.7,270.5
XS GIS Cut Line= 2
1649132.73807433441987.6019438791649565.09235771441823.067119369
#Sta/Elev= 30
       0 1130.17      25 1120.73      55 1107.47    63.5 1105.25      67 1103.67
    91.8 1085.09    97.8 1081.01   110.6 1073.34   116.6 1071.07   122.8 1070.25
   166.2 1069.03   196.2 1068.62   225.1 1068.89     239 1067.78  245.37 1066.32
   247.6 1065.85  254.76 1066.35   260.4 1066.28   264.7 1067.55   277.5 1075.88
   281.8 1078.29   307.5 1089.83   324.6 1099.62   339.1 1105.04   350.3 1109.79
   367.7 1118.94   388.8 1128.12   424.7 1146.37   444.4 1155.16462.6034 1162.53
#Mann= 3 ,-1,0
       0      .1       0  245.37    .045       0  254.76      .1       0
Bank Sta=245.37,254.76
XS Rating Curve= 0 ,0
Exp/Cntr(USF)=0,0
Exp/Cntr=0.3,0.1

Type RM Length L Ch R = 1 ,6003    ,261.3,260.3,254.8
XS GIS Cut Line= 2
1649209.50404467442143.5681309081649619.24619903442147.070200604
#Sta/Elev= 30
       0 1113.86    10.6 1111.13    30.6 1107.17    62.6    1096    74.6 1090.95
    86.6 1085.07    98.6  1077.9   110.6 1071.41   118.6 1068.53   126.7 1067.21
   138.6 1066.72   178.6 1066.67   198.6 1065.13   226.6 1065.58   238.6 1063.55
   242.6 1063.02  247.15 1063.55   250.6 1065.17   254.6 1068.35   266.6 1081.81
   270.6 1085.61   274.6 1088.81   294.6 1102.95   298.6 1104.88   314.6 1110.35
   322.6 1113.76   342.6    1124   352.7 1128.43   382.6  1142.9409.7571 1154.17
#Mann= 5 ,-1,0
       0      .1       0      40     .06       0     140      .1       0
   238.6    .045       0  247.15      .1       0
Bank Sta=238.6,247.15
XS Rating Curve= 0 ,0
Exp/Cntr(USF)=0,0
Exp/Cntr=0.3,0.1

Type RM Length L Ch R = 1 ,5742    ,298.3,297.7,295.8
XS GIS Cut Line= 3
1649244.06414142442548.5166698211649333.47073706442435.090391773
1649707.11024122442269.621468502
#Sta/Elev= 30
       0 1128.63    20.3 1122.58    45.8 1110.97    81.5 1102.71    86.6 1099.88
   101.8 1089.49     112 1084.14   116.8 1082.55     131 1080.29   151.7 1073.39
   172.6 1069.06   204.2  1066.4   226.1 1065.43   243.6 1063.64   252.3 1063.72
   260.5 1061.65   265.4 1061.21   274.2 1061.66   287.3 1063.74   324.2 1063.29
   331.1  1063.8   335.4 1065.06   339.8 1067.46   344.2 1070.92   352.9 1079.08
   363.6 1090.51   374.8 1098.89   444.8 1117.93   523.5  1146.5553.0664 1156.17
#Mann= 4 ,-1,0
       0      .1       0  154.43     .06       0   260.5    .045       0
   274.2      .1       0
Bank Sta=260.5,274.2
XS Rating Curve= 0 ,0
Exp/Cntr(USF)=0,0
Exp/Cntr=0.3,0.1

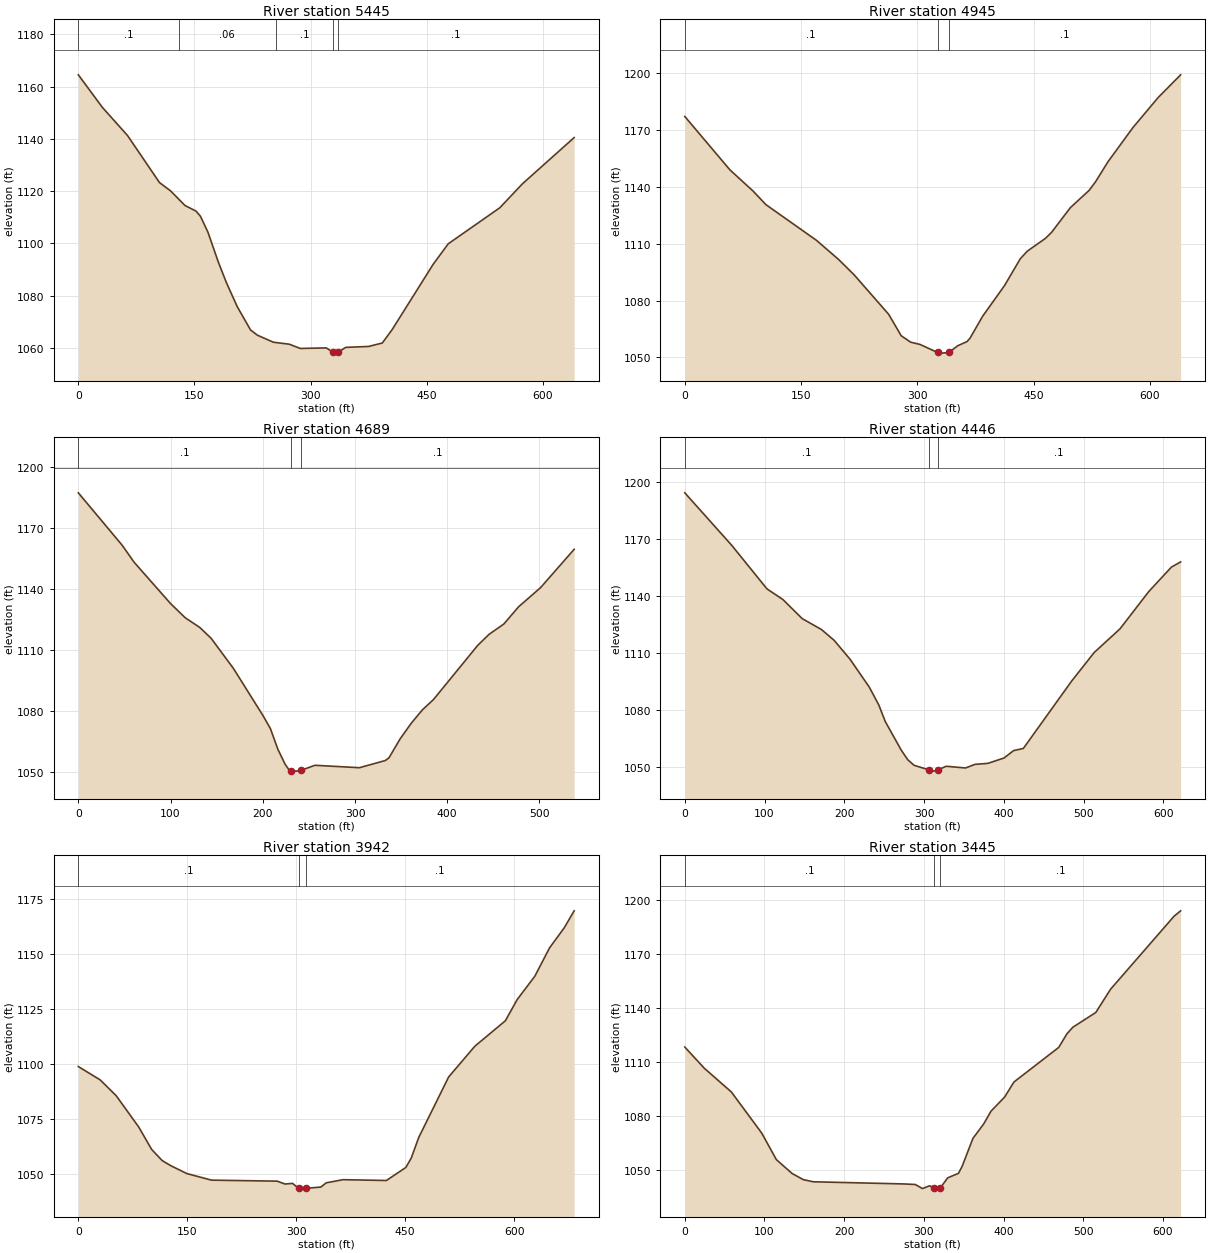
Type RM Length L Ch R = 1 ,5445    ,493.2,500.1,503
XS GIS Cut Line= 6
1649343.03123434442768.0465203371649503.11752833442656.663212925
1649576.20235592442616.5484637621649672.67001076442586.222736999
1649741.47466317 442555.323848681649888.98125793442443.438573763
#Sta/Elev= 30
       0 1164.52    30.9 1152.12    63.5 1141.31   104.8  1123.3   119.2  1120.1
   137.7 1114.53   152.1 1112.36   157.7  1110.4   167.4 1104.29   180.9 1092.77
   191.4 1084.88   205.3 1075.77   222.4 1066.91   231.2 1064.91   251.9 1062.21
   272.5 1061.45   286.7 1059.82   320.3 1060.04   328.6 1058.39   332.8 1058.04
  335.64 1058.39   345.2 1060.24   374.8 1060.59   392.5 1061.91   405.2 1067.02
   458.2 1092.02   477.6 1099.85   544.3 1113.66   573.5 1122.83640.2725 1140.51
#Mann= 5 ,-1,0
       0      .1       0  129.56     .06       0  255.05      .1       0
   328.6    .045       0  335.64      .1       0
Bank Sta=328.6,335.64
XS Rating Curve= 0 ,0
Exp/Cntr(USF)=0,0
Exp/Cntr=0.3,0.1

Type RM Length L Ch R = 1 ,4945    ,254.9,255.2,255
XS GIS Cut Line= 6
1649544.43240634442986.3302045021649652.28914601442952.052714005
1649745.50155801442936.092115998  1649820.202196442947.213812917
1649993.44299126442971.9647476671650172.87143818442997.598226592
#Sta/Elev= 30
       0 1177.23    58.4 1148.95    87.8 1137.95   104.6 1130.69   169.8 1111.84
   198.2 1101.79   218.5 1093.58     263 1072.75   279.1 1061.46   291.3 1058.06
   303.4 1056.87     326 1052.62   331.7 1052.28   340.9 1052.63   351.9 1056.15
     364 1058.37     368 1060.24   384.2 1071.77   412.5 1088.01   432.8 1102.15
   441.9 1106.16     465 1112.81   473.1 1116.06   497.3 1129.08   521.6 1138.25
   529.7 1142.69   545.8  1153.3   578.1 1171.41   610.5  1187.2639.5157 1199.21
#Mann= 3 ,-1,0
       0      .1       0     326    .045       0   340.9      .1       0
Bank Sta=326,340.9
XS Rating Curve= 0 ,0
Exp/Cntr(USF)=0,0
Exp/Cntr=0.3,0.1

Type RM Length L Ch R = 1 ,4689    ,243.4,243.1,241.5
XS GIS Cut Line= 2
1649568.77466289443177.9213107561650104.02807956443228.332989889
#Sta/Elev= 30
       0 1187.42    47.5 1161.63    60.5 1153.23    99.8 1132.97   115.9 1125.89
   131.9 1121.04     144 1115.77   168.1 1100.99   200.1  1077.8   208.3 1071.28
   216.3 1061.19   224.3 1053.67   228.3 1051.08  230.88 1050.65   236.4 1050.35
  240.96 1050.66   256.5 1053.23   304.7 1052.03   332.8 1055.56   336.8 1056.88
   348.9 1066.22   360.9 1073.88     373  1080.5     385 1085.56   433.2 1112.36
   445.3  1117.7   461.4 1122.82   477.4 1131.29   501.2 1140.73537.6221 1159.61
#Mann= 3 ,-1,0
       0      .1       0  230.88    .045       0  240.96      .1       0
Bank Sta=230.88,240.96
XS Rating Curve= 0 ,0
Exp/Cntr(USF)=0,0
Exp/Cntr=0.3,0.1

Type RM Length L Ch R = 1 ,4446    ,507.3,504.2,503.4
XS GIS Cut Line= 6
1649521.30220325 443427.569479511649618.18193075443432.632461503
1649708.63647425443439.3962275091649786.01066335443443.644250512
1649885.55869259443433.5629058331650139.48502201 443399.13088809
#Sta/Elev= 30
       0 1194.53    58.9 1166.87     103 1143.98     123 1138.37   147.1 1128.35
   171.2 1122.62   187.2  1116.9   207.2 1106.92   231.3 1092.25   243.3 1082.77
   251.3 1074.16   271.3 1059.12   279.4  1054.1   287.4 1051.12  306.58 1048.66
   311.5 1048.06  317.12 1048.68   327.6 1050.62   351.8 1049.72   363.8 1051.62
     380 1052.15   400.1 1054.96   412.2 1058.87   424.4 1060.01   484.9 1095.45
   513.2  1110.5   545.5 1122.93   581.7 1142.62     610 1155.45621.5171 1158.17
#Mann= 3 ,-1,0
       0      .1       0  306.58    .045       0  317.12      .1       0
Bank Sta=306.58,317.12
XS Rating Curve= 0 ,0
Exp/Cntr(USF)=0,0
Exp/Cntr=0.3,0.1

Type RM Length L Ch R = 1 ,3942    ,489.6,497.2,495.8
XS GIS Cut Line= 6
1649556.87693526 444056.267697171649645.45188934444014.857346922
1649719.66433933443964.2327762541649836.45511626443822.768820345
1649923.87685743443780.085834846 1650133.6605586443737.981916428
#Sta/Elev= 30
       0 1098.96    30.1 1092.88    52.1 1085.72    83.1 1071.51     101 1061.28
   115.5 1056.23   127.3 1053.93   149.4 1050.34   183.3 1047.36   273.8  1046.9
   284.5  1045.6   294.9 1045.89   303.1 1043.65   305.5 1043.28  313.38 1043.64
   333.8 1044.22   341.3 1046.15   364.5 1047.57   424.1  1047.2   450.9 1053.13
   458.3 1057.38   468.6 1066.72   509.8 1094.22   545.9 1108.19   587.9 1119.75
   604.1 1129.35   628.4 1139.95   648.6 1152.79   668.9 1161.95682.5702 1169.67
#Mann= 3 ,-1,0
       0      .1       0   303.1    .045       0  313.38      .1       0
Bank Sta=303.1,313.38
XS Rating Curve= 0 ,0
Exp/Cntr(USF)=0,0
Exp/Cntr=0.3,0.1

Type RM Length L Ch R = 1 ,3445    ,473.5,480.1,481.7
XS GIS Cut Line= 6
1649746.30536218 444421.243673251649816.89970918444353.727076009
 1649880.4760256444289.0769428461649939.54316467444238.833276927
1650028.10762009444192.1824515911650253.99037042444071.444504082
#Sta/Elev= 30
       0  1118.5    24.6 1106.67    58.4 1093.57    96.6 1070.67   114.9 1055.98
   134.7 1048.26   148.9 1044.83   161.1 1043.68   275.6 1042.47   289.2 1042.17
   298.2 1039.92   307.2 1041.46  312.33 1040.38   316.3  1039.6   320.8 1040.38
   329.8 1045.84   343.4 1048.39     348 1052.24   361.5 1067.74   375.1 1075.85
   384.2 1082.89   401.2 1090.67     413 1099.08   469.2  1118.3   479.4  1125.8
   486.9 1129.49   515.7 1137.69   534.2 1150.59     614 1191.19622.1282 1194.14
#Mann= 3 ,-1,0
       0      .1       0  312.33    .045       0   320.8      .1       0
Bank Sta=312.33,320.8
XS Rating Curve= 0 ,0
Exp/Cntr(USF)=0,0
Exp/Cntr=0.3,0.1

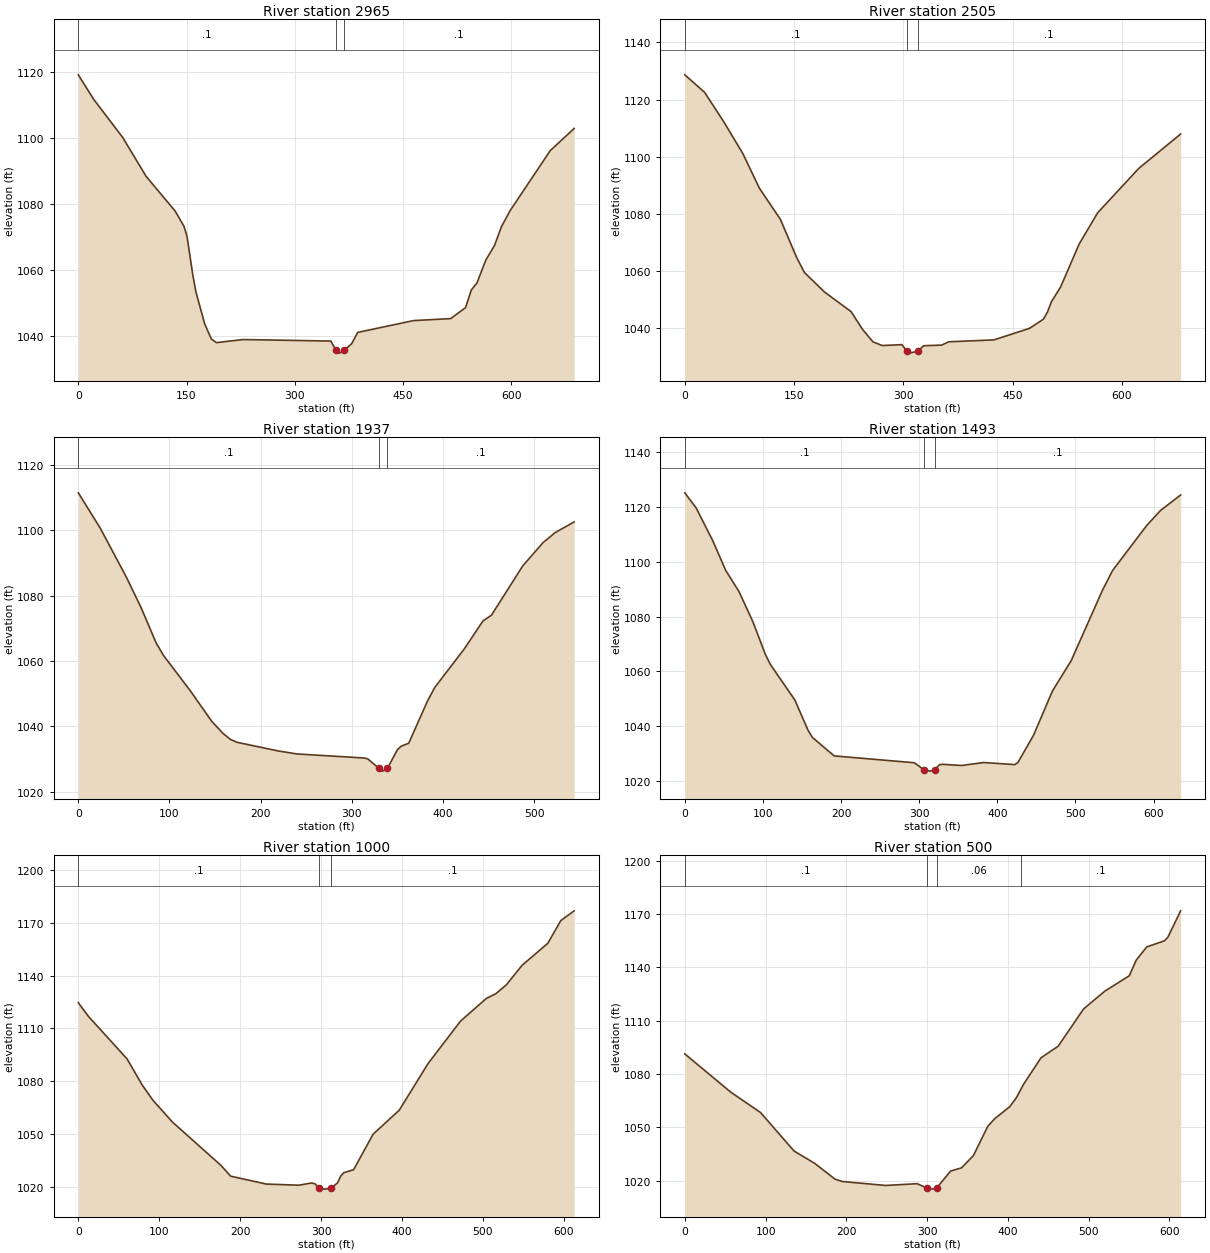
Type RM Length L Ch R = 1 ,2965    ,465.1,459.5,451.4
XS GIS Cut Line= 6
1649795.07790242 444533.911755011649904.24697542444546.750968173
1650012.16801943   444568.722709 1650211.4947205444627.533943087
1650375.03934093 444622.683559091650470.08212984444611.645851508
#Sta/Elev= 30
       0 1119.15    21.2 1111.76    61.5  1100.2    93.7 1088.49   134.3 1077.88
   146.5 1073.26   150.6 1070.32   158.8  1058.4   162.9 1053.51   175.1  1043.8
   184.3  1039.2   191.4 1038.08   228.4 1039.01     350 1038.55   357.2 1035.76
   362.4  1034.9  368.53 1035.74     379  1037.8   387.3 1041.17   464.6 1044.75
   516.1 1045.35   536.7 1048.66   544.7 1053.99   552.7 1056.21   564.7 1063.02
   576.7 1067.39   586.4 1073.11   598.1  1077.9   654.2 1096.22687.2847 1102.91
#Mann= 3 ,-1,0
       0      .1       0   357.2    .045       0  368.53      .1       0
Bank Sta=357.2,368.53
XS Rating Curve= 0 ,0
Exp/Cntr(USF)=0,0
Exp/Cntr=0.3,0.1

Type RM Length L Ch R = 1 ,2505    ,555.6,567.9,570.4
XS GIS Cut Line= 6
1649992.55683817445138.2950606791650077.56257367445084.819445834
1650142.33245726445024.0961420831650192.07284334444967.773748174
1650302.22321358444809.4262958321650474.44170117444667.600792095
#Sta/Elev= 30
       0 1128.68    27.1 1122.58    53.2 1112.39    79.8  1101.1   102.4 1089.05
   131.3 1078.13   153.5 1064.86   164.2 1059.58   191.9 1052.73   228.2 1045.92
     244 1039.69   258.4  1035.3   271.2 1034.03   298.1 1034.35   305.1 1032.03
     308 1031.38   319.7 1032.01   327.8 1033.96   352.6 1034.19   362.5 1035.34
   424.4 1036.01   473.4 1040.05   492.4 1043.26   497.9 1045.75   503.3 1049.32
   515.9 1054.49   541.4  1069.5   566.8 1080.44   623.1 1095.93680.7181 1107.99
#Mann= 3 ,-1,0
       0      .1       0   305.1    .045       0   319.7      .1       0
Bank Sta=305.1,319.7
XS Rating Curve= 0 ,0
Exp/Cntr(USF)=0,0
Exp/Cntr=0.3,0.1

Type RM Length L Ch R = 1 ,1937    ,441.7,444.7,442.6
XS GIS Cut Line= 3
1650016.41430596445227.8063590381650461.17875859445314.944429115
1650542.84567878445275.311953138
#Sta/Elev= 30
       0 1111.53    24.2 1100.64    52.7 1085.72      69  1076.3    85.3 1065.62
    93.4 1061.76   123.1 1050.84   146.4 1041.56   158.7 1037.89   166.8 1036.05
   174.2 1035.15   219.8 1032.48   240.2 1031.58   313.5 1030.35   317.6 1030.08
   329.9 1027.15   333.9 1026.33  339.07 1027.14   350.2 1032.96   354.3 1033.97
   362.5 1034.88   382.8 1047.62     391 1051.92   423.6  1063.8     444 1072.33
   453.2 1074.04   487.6 1089.16   509.8 1096.27   523.2 1099.36543.9957 1102.63
#Mann= 3 ,-1,0
       0      .1       0   329.9    .045       0  339.07      .1       0
Bank Sta=329.9,339.07
XS Rating Curve= 0 ,0
Exp/Cntr(USF)=0,0
Exp/Cntr=0.3,0.1

Type RM Length L Ch R = 1 ,1493    ,493.8,492.7,492.1
XS GIS Cut Line= 6
  1650070.433979 445769.565779761650324.71168567445691.798218757
1650425.93392417445706.3224679231650503.94032983445707.122335091
 1650594.1970391445695.3516893391650689.01837176445673.472468004
#Sta/Elev= 30
       0 1125.19    14.5  1119.7    35.6 1107.83    52.5 1096.81    69.4 1089.14
    87.2 1078.12   103.2 1066.17   109.4 1062.61     141 1049.51   157.7 1038.55
   163.5 1035.87   191.2 1029.17   293.8 1026.67   305.9 1024.13     314 1023.61
  319.72 1024.12   326.1 1025.97   330.1  1026.1   354.4 1025.67   382.5 1026.75
   422.5 1025.99   426.5 1026.81   446.5 1036.77   470.7  1052.9   494.6 1063.93
   534.4 1089.48   547.5  1096.8   591.3 1113.28   609.1 1118.79634.6729 1124.41
#Mann= 3 ,-1,0
       0      .1       0   305.9    .045       0  319.72      .1       0
Bank Sta=305.9,319.72
XS Rating Curve= 0 ,0
Exp/Cntr(USF)=0,0
Exp/Cntr=0.3,0.1

Type RM Length L Ch R = 1 ,1000    ,502.4,500,496.1
XS GIS Cut Line= 6
1650207.92583001446158.6742535081650464.14710234446154.850442261
1650564.13607559446153.357335001 1650639.1277235446152.239555091
1650726.63542251446152.0896210071650820.54304309 446151.40950425
#Sta/Elev= 30
       0 1124.64    12.2 1117.02    60.2 1092.73    79.2 1077.69    92.2 1069.22
   116.2 1056.87   176.2 1032.25   188.2  1026.1   232.2 1021.62   272.2 1020.97
   288.2 1022.22   292.2 1021.83  297.97 1019.17   304.2 1018.74   312.2  1019.2
   320.2 1022.27   324.2 1026.14   328.2 1028.08   340.2 1029.79   364.2 1049.94
   396.5 1063.54   432.2 1090.09   472.2 1114.14   504.2 1127.07   515.8 1129.72
   528.8 1134.73   548.2 1145.81   580.2 1158.42   596.2  1171.3612.6678 1176.82
#Mann= 3 ,-1,0
       0      .1       0  297.97    .045       0   312.2      .1       0
Bank Sta=297.97,312.2
XS Rating Curve= 0 ,0
Exp/Cntr(USF)=0,0
Exp/Cntr=0.3,0.1

Type RM Length L Ch R = 1 ,500     ,465.5,467.1,468.1
XS GIS Cut Line= 6
1650358.90912384446779.0946005881650440.15469626446732.316150844
1650667.64439876446601.3400348421650734.96250559446567.950009748
1650815.59981151446532.6544766721650902.77450593446496.535454422
#Sta/Elev= 30
       0 1091.26    56.8 1069.77    93.8 1058.25   135.2 1036.64   160.9 1029.64
     186 1020.77   195.2 1019.45   248.8 1017.23   287.6 1018.23   299.8  1015.8
     306 1015.17   311.8  1015.8   329.1 1025.35   342.5 1027.13   357.2 1033.99
   375.1 1050.52   383.6 1054.79     402 1061.43   410.4 1066.55   419.3 1074.11
   440.9 1089.03   462.2 1095.58   493.8 1116.62     520 1126.56   550.3 1135.24
   558.9 1144.06   571.9 1151.47   593.6 1154.86   597.9  1156.8   613.8 1171.76
#Mann= 4 ,-1,0
       0      .1       0   299.8    .045       0   311.8     .06       0
  416.25      .1       0
Bank Sta=299.8,311.8
XS Rating Curve= 0 ,0
Exp/Cntr(USF)=0,0
Exp/Cntr=0.3,0.1

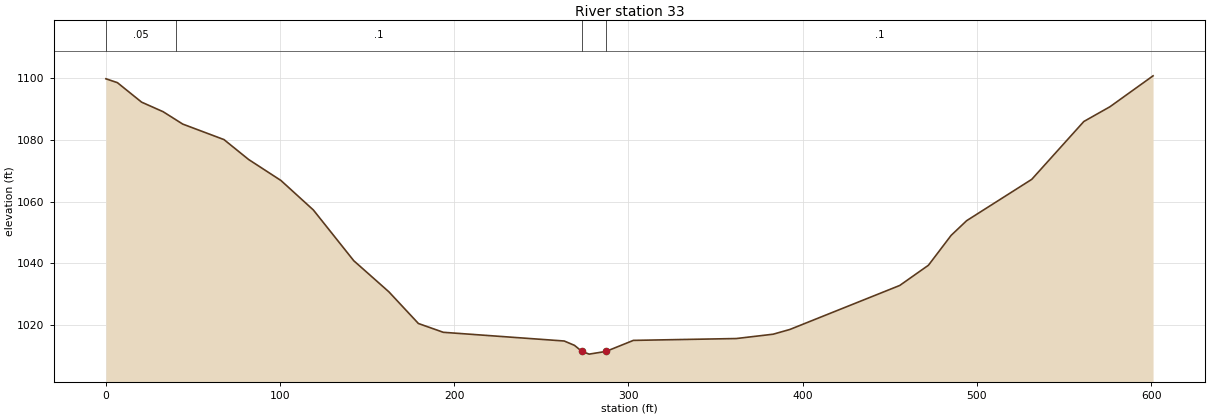
Type RM Length L Ch R = 1 ,33      ,,,
XS GIS Cut Line= 4
1650601.73627539447255.1375559931650699.14943183447089.668632723
1650964.70036514447000.2620370851651020.74629077446884.166905435
#Sta/Elev= 30
       0 1099.75     6.6  1098.5    20.5 1092.18    32.9 1089.07    44.1 1085.08
    67.8 1080.05    81.9 1073.62   100.5  1066.8   119.1 1057.25   142.3 1040.81
   162.4 1030.77   179.4 1020.48   193.7 1017.63   263.1 1014.81     269  1013.4
   273.2 1011.47   277.4 1010.56  287.12 1011.44   302.8 1015.01   361.9 1015.61
     383 1017.01   392.6 1018.54   455.7  1032.8   472.2 1039.36   485.2 1049.02
   494.1 1053.78   531.5 1067.18   561.4 1085.92   576.4  1090.7601.1272 1100.71
#Mann= 4 ,-1,0
       0     .05       0      40      .1       0   273.2    .045       0
  287.12      .1       0
Bank Sta=273.2,287.12
XS Rating Curve= 0 ,0
Exp/Cntr(USF)=0,0
Exp/Cntr=0.3,0.1
LCMann Table=0

Chan Stop Cuts=-1
Use User Specified Reach Order=0
Composite Channel Slope=5